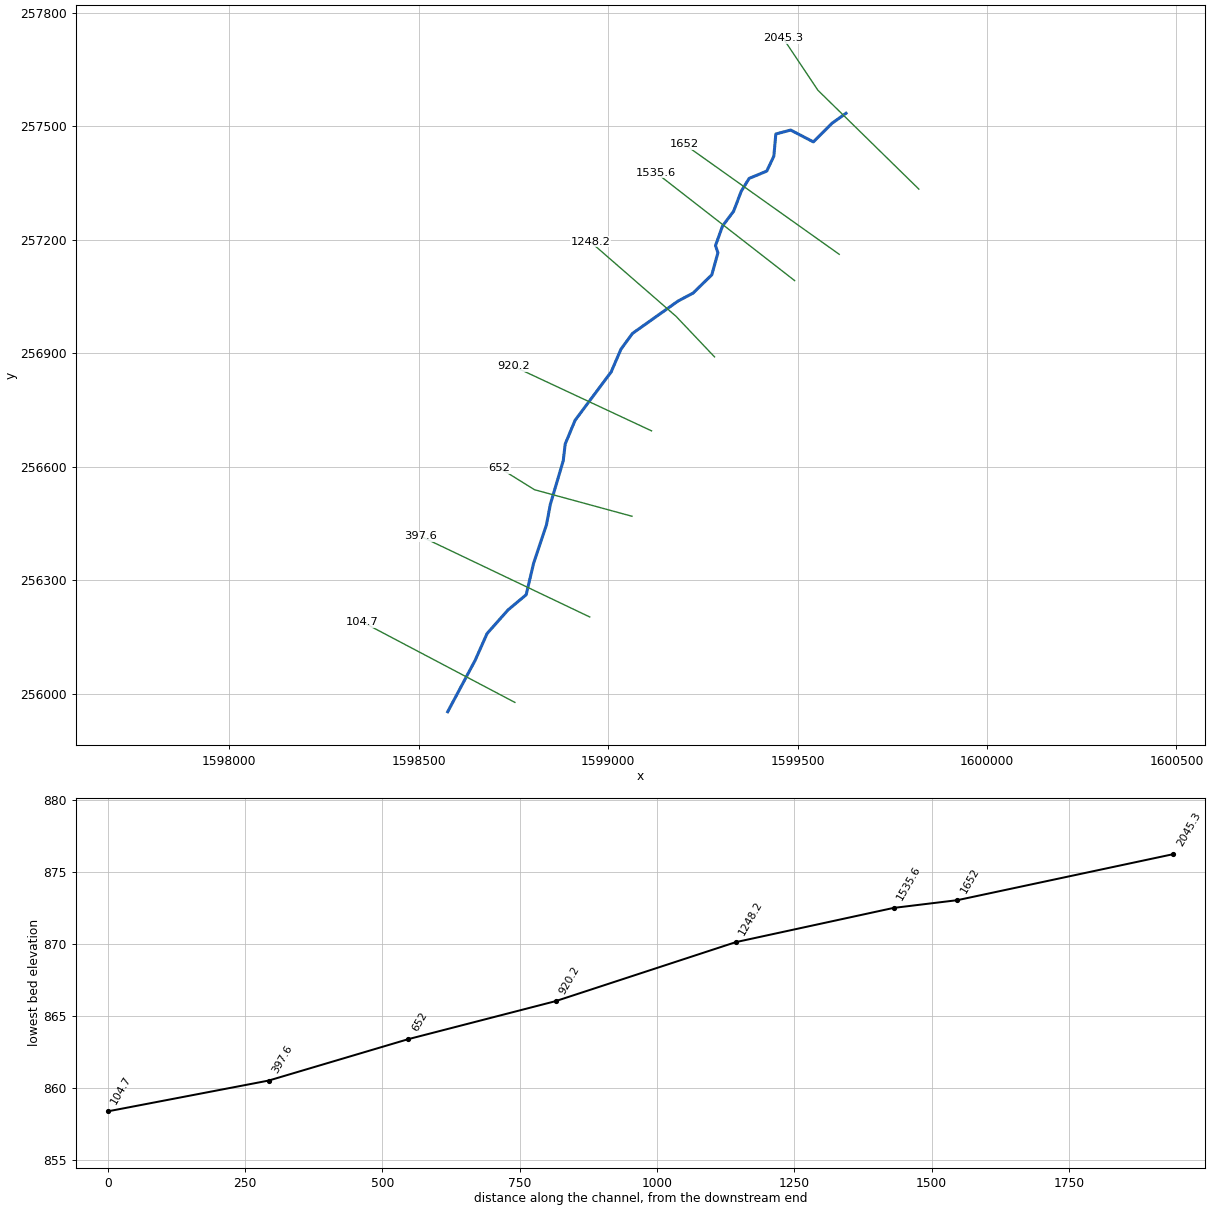
--- BIGRN1.prj (project) ---

Proj Title=BIGRN1
Current Plan=p01
Geom File=g01
Flow File=f01
Plan File=p01
DSS Export Rating Curves=0
DSS Export Rating Curve Sorted=0
DSS Export Volume Flow Curves=0
DXF OffsetX=0
DXF OffsetY=0
DXF ScaleX=0
DXF ScaleY=0

--- BIGRN1.p01 (plan) ---

Plan Title=Floodplain
Program Version=4.00
Geom File=g01
Flow File=f01
K Sum by GR=0
Std Step Tol=0.01
Critical Tol=0.01
Num of Std Step Trials=20
Max Error Tol=0.3
Flow Tol Ratio=0.001
Split Flow NTrial=30
Split Flow Tol=0.02
Split Flow Ratio=0.02
Log Output Level=0
Friction Slope Method=1
Unsteady Friction Slope Method=2
Unsteady Bridges Friction Slope Method=1
Global Log Level=0
CheckData=False
Run HTab=0
Run UNet=0
Run PostProcess=0
UNET Theta=0
UNET Theta Warmup=0
UNET ZTol=0
UNET ZSATol=0
UNET MxIter=0
UNET MaxInSteps=0
UNET DtIC=0
UNET DtMin=0
UNET MaxCRTS=0
UNET WFStab=0
UNET SFStab=0
UNET WFX=0
UNET SFX=0
UNET DSS MLevel=0
UNET DZMax Abort=0
UNET Convert EG Bridges=0
UNET Use Existing IB Tables=0
UNET Froude Limit=0
UNET Froude Power=0
Write IC File=0
Echo Input=False
Echo Output=False
Write Detailed=0

--- BIGRN1.f01 (steady flow) ---

Flow Title=NFF Regression Equation
Program Version=4.00
Number of Profiles=1
Profile Names=P100yr
River Rch & RM=BIGRN1,Main      ,2045.3
672.2440
River Rch & RM=BIGRN1,Main      ,397.6
700.6610
River Rch & RM=BIGRN1,Main      ,104.7
702.7609
Boundary for River Rch & Prof#=BIGRN1,Main      ,1
Up Type=0
Dn Type=3
Dn Slope=0.009215

--- BIGRN1.g01 (geometry) ---

Geom Title=USGS 10m DEM
Program Version=4.10

River Reach=BIGRN1          ,Main
Reach XY= 30
     1599627.696      257534.629     1599591.155      257508.528
     1599541.565      257458.937     1599481.534      257490.258
     1599442.384      257479.818     1599437.191      257421.197
     1599418.417      257381.704     1599371.913      257362.366
     1599351.033      257328.436     1599331.029      257275.725
     1599301.774      257236.735     1599283.172      257184.885
     1599289.535      257165.795     1599273.359      257107.451
     1599224.018      257059.259     1599184.369      257038.167
     1599063.927      256952.447     1599033.545       256910.78
     1599007.671      256850.608     1598912.548      256722.909
     1598886.447      256660.269     1598881.228      256615.898
     1598847.297      256501.057     1598836.857      256446.247
     1598802.927      256344.455     1598783.328      256261.475
     1598735.368      256221.327     1598680.255      256159.143
     1598648.935      256088.673     1598576.212      255952.156

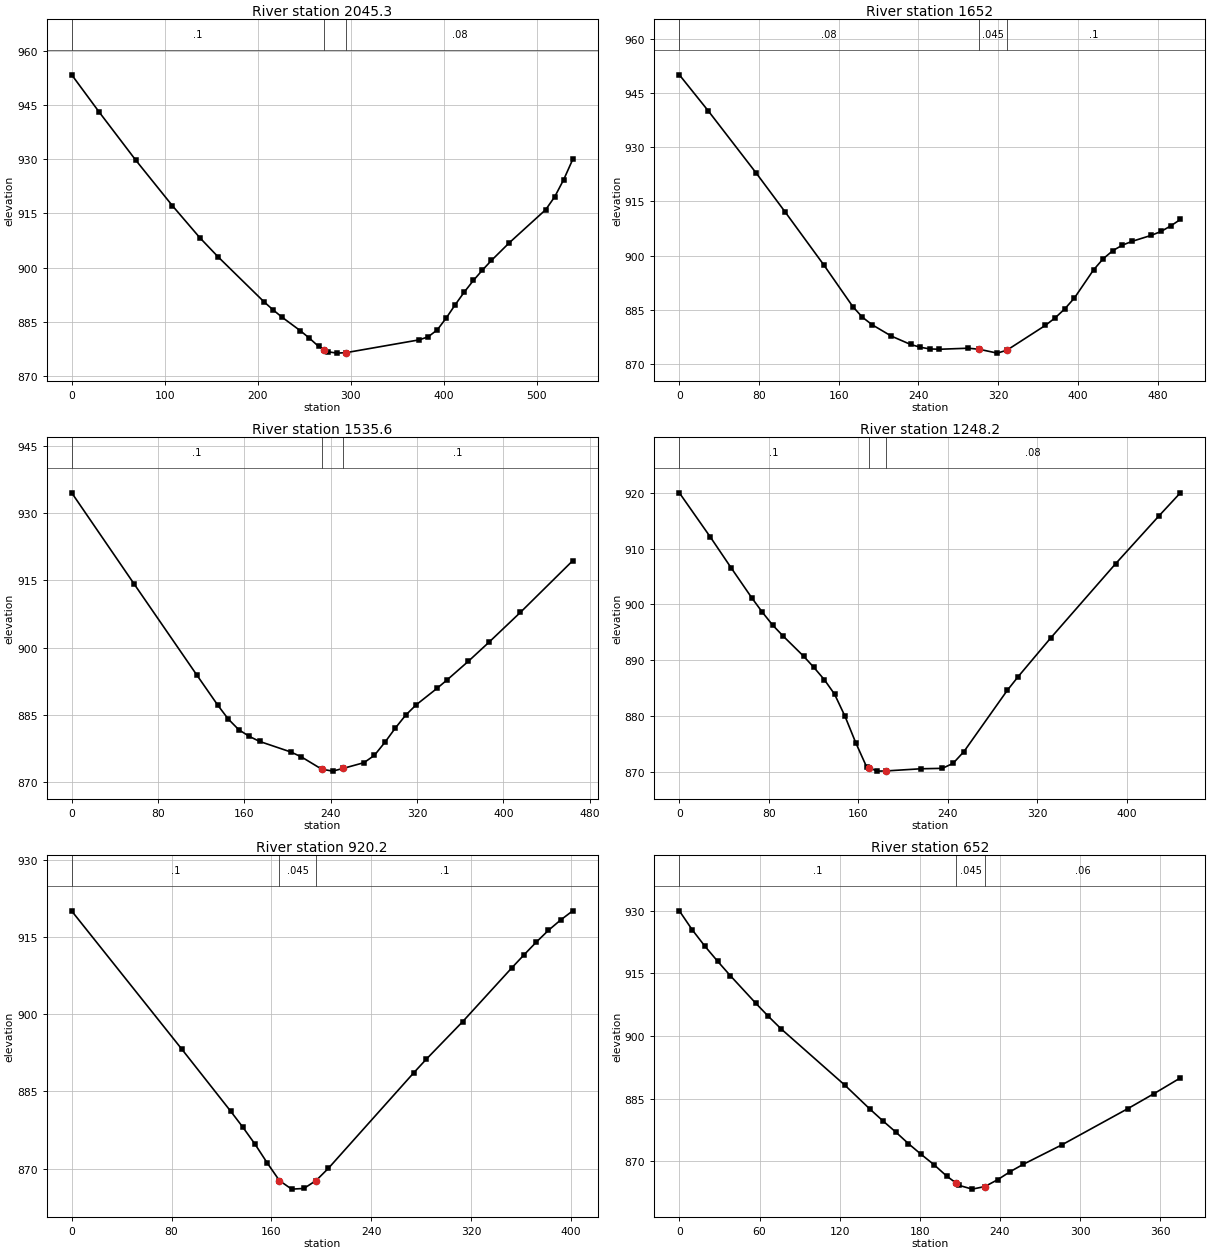
Type RM Length L Ch R = 1 ,2045.3  ,387.7,393.3,395.1
XS GIS Cut Line= 3
     1599819.973      257334.019     1599553.365      257595.641
     1599461.744       257732.96
#Sta/Elev= 30
       0  953.47    29.5  943.14    68.8   929.8   108.1  917.19   137.6   908.3
   157.3  902.97   206.4  890.56   216.3  888.28   226.1  886.21   245.7  882.47
   255.6  880.37   265.4   878.1   271.7  877.16   275.2  876.63   285.1  876.24
   294.9  876.37   373.5  879.92   383.2  880.77     393   882.7   402.7  886.02
   412.4  889.72   422.1  893.22   431.8   896.4   441.5  899.28   451.2  901.96
   470.6  906.91   509.5  916.04   519.2  919.61   528.9   924.4   538.6     930
#Mann= 3 , 0 , 0
       0      .1       0   271.7    .045       0   294.9     .08       0
Bank Sta=271.7,294.9
XS Rating Curve= 0 ,0
Exp/Cntr=0.3,0.1

Type RM Length L Ch R = 1 ,1652    ,117.1,116.4,115.1
XS GIS Cut Line= 2
       1599609.8      257161.681     1599200.104      257453.267
#Sta/Elev= 30
       0     950      29  940.04    77.4  922.74   106.4     912   145.1  897.39
   174.1  885.91   183.7  882.98   193.4  880.91   212.8  877.75   232.1  875.44
   241.8  874.67   251.4   874.2   261.1  874.11   290.1   874.4     301  874.11
   319.1  873.04   328.8  873.85   367.5  880.73   377.2  882.79   386.8  885.25
   396.5  888.27   415.8  896.08   425.5  899.15   435.2   901.4   444.8  902.91
   454.5  903.96   473.8  905.62   483.5  906.69   493.2  908.21   502.9     910
#Mann= 3 , 0 , 0
       0     .08       0     301    .045       0   328.8      .1       0
Bank Sta=301,328.8
XS Rating Curve= 0 ,0
Exp/Cntr=0.3,0.1

Type RM Length L Ch R = 1 ,1535.6  ,288.5,287.4,286
XS GIS Cut Line= 2
     1599492.111      257092.158     1599126.072      257377.587
#Sta/Elev= 25
       0  934.54      58  914.16     116  893.89   135.4  887.18     145  884.12
   154.7  881.75   164.4  880.26   174.1  879.12   203.1  876.76   212.8  875.67
   231.6  872.94   241.8   872.5   251.4   873.1   270.8  874.39   280.4  876.01
   290.1   878.9   299.8  882.09   309.4  884.97   319.1  887.27   338.5  890.96
   348.1   892.9   367.5  896.99   386.8  901.28   415.8  907.91   464.2  919.41
#Mann= 3 , 0 , 0
       0      .1       0   231.6    .045       0   251.4      .1       0
Bank Sta=231.6,251.4
XS Rating Curve= 0 ,0
Exp/Cntr=0.3,0.1

Type RM Length L Ch R = 1 ,1248.2  ,321.7,328,334.5
XS GIS Cut Line= 3
     1599280.625      256890.469     1599178.764      256997.961
     1598952.644      257195.065
#Sta/Elev= 27
       0     920    27.8  912.05    46.3  906.56    64.8  901.17      74  898.66
    83.3  896.32    92.6  894.37   111.1  890.72   120.3  888.71   129.6  886.52
   138.8  883.91   148.1  879.96   157.8  875.18   167.4   870.9   169.4  870.74
   177.1  870.12   184.4  870.15   215.8  870.54   235.2  870.62   244.8  871.52
   254.5  873.63   293.2  884.59   302.9  887.04   331.9  893.95     390  907.27
   428.7  915.83     448     920
#Mann= 3 , 0 , 0
       0      .1       0   169.4    .045       0   184.4     .08       0
Bank Sta=169.4,184.4
XS Rating Curve= 0 ,0
Exp/Cntr=0.3,0.1

Type RM Length L Ch R = 1 ,920.2   ,263.9,268.1,271.6
XS GIS Cut Line= 2
     1599114.268      256694.953     1598750.703      256865.172
#Sta/Elev= 20
       0     920    88.1  893.22   127.3  881.16   137.1  878.04   146.9  874.73
   156.7  871.08   166.4  867.68   176.2  866.02     186  866.15   195.8  867.69
   205.6  870.05   274.2  888.65     284  891.22   313.3  898.55   352.5  908.95
   362.3  911.48   372.1  913.94   381.9  916.25   391.6  918.24   401.4  920.04
#Mann= 3 , 0 , 0
       0      .1       0   166.4    .045       0   195.8      .1       0
Bank Sta=166.4,195.8
XS Rating Curve= 0 ,0
Exp/Cntr=0.3,0.1

Type RM Length L Ch R = 1 ,652     ,258.5,254.4,250.2
XS GIS Cut Line= 3
     1599062.761      256469.125     1598805.369      256539.328
     1598713.456      256596.529
#Sta/Elev= 27
       0     930     9.5  925.52    19.1  921.54    28.6  917.95    38.1   914.5
    57.2  907.88    66.7  904.72    76.2  901.73   123.9  888.26   142.9  882.46
   152.4  879.71     162  877.04   171.5  874.26     181   871.7   190.6  869.23
   200.1   866.5   207.3   864.8   209.6  864.26   219.2  863.38   228.7     864
   238.2  865.63   247.7  867.58   257.3   869.3   286.5  874.01   335.7  882.65
   355.4  886.26     375     890
#Mann= 3 , 0 , 0
       0      .1       0   207.3    .045       0   228.7     .06       0
Bank Sta=207.3,228.7
XS Rating Curve= 0 ,0
Exp/Cntr=0.3,0.1

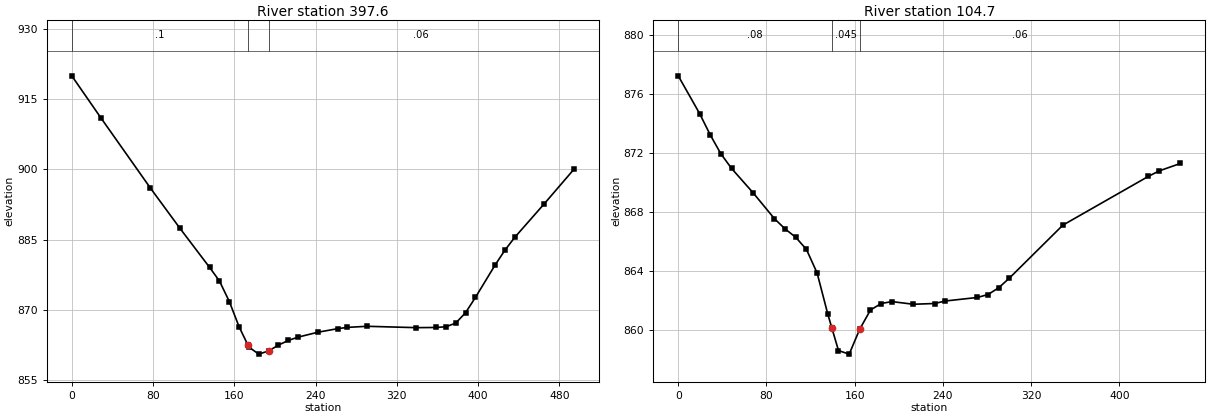
Type RM Length L Ch R = 1 ,397.6   ,293.9,292.9,291.4
XS GIS Cut Line= 2
     1598951.162      256202.833     1598505.177      256415.932
#Sta/Elev= 30
       0     920    29.1  910.88    77.5  895.98   106.6  887.37   135.7  879.04
   145.4  876.13   155.1  871.75   164.8  866.31   173.4  862.45   174.4     862
   184.1   860.5   193.8  861.18   203.5  862.43   213.2  863.43   222.9  864.14
   242.3  865.18   261.7  865.94   271.4  866.22   290.8  866.45   339.2  866.16
   358.6   866.2   368.3  866.35     378  867.13   387.7  869.36   397.4  872.62
   416.8  879.56   426.4  882.71   436.1  885.46   465.2  892.65   494.3     900
#Mann= 3 , 0 , 0
       0      .1       0   173.4    .045       0   193.8     .06       0
Bank Sta=173.4,193.8
XS Rating Curve= 0 ,0
Exp/Cntr=0.3,0.1

Type RM Length L Ch R = 1 ,104.7   ,104.4,104.7,105.1
XS GIS Cut Line= 2
     1598753.464      255977.009     1598350.928      256189.532
#Sta/Elev= 30
       0  877.22    19.4  874.66      29  873.22    38.7  871.93    48.4  870.94
    67.8   869.3    87.2  867.54    96.8  866.85   106.5  866.28   116.2  865.46
   125.9  863.86   135.6  861.07   139.4   860.1   145.3   858.6     155  858.36
   164.6  860.06   174.3  861.35     184  861.79   193.7  861.92   213.1  861.74
   232.4  861.79   242.1  861.96   271.2   862.2   280.9   862.4   290.6  862.86
   300.2  863.51   348.7   867.1   426.1   870.4   435.8  870.77   455.2  871.28
#Mann= 3 , 0 , 0
       0     .08       0   139.4    .045       0   164.6     .06       0
Bank Sta=139.4,164.6
XS Rating Curve= 0 ,0
Exp/Cntr=0.3,0.1

Chan Stop Cuts=-1
Use User Specified Reach Order=0
Composite Channel Slope=5